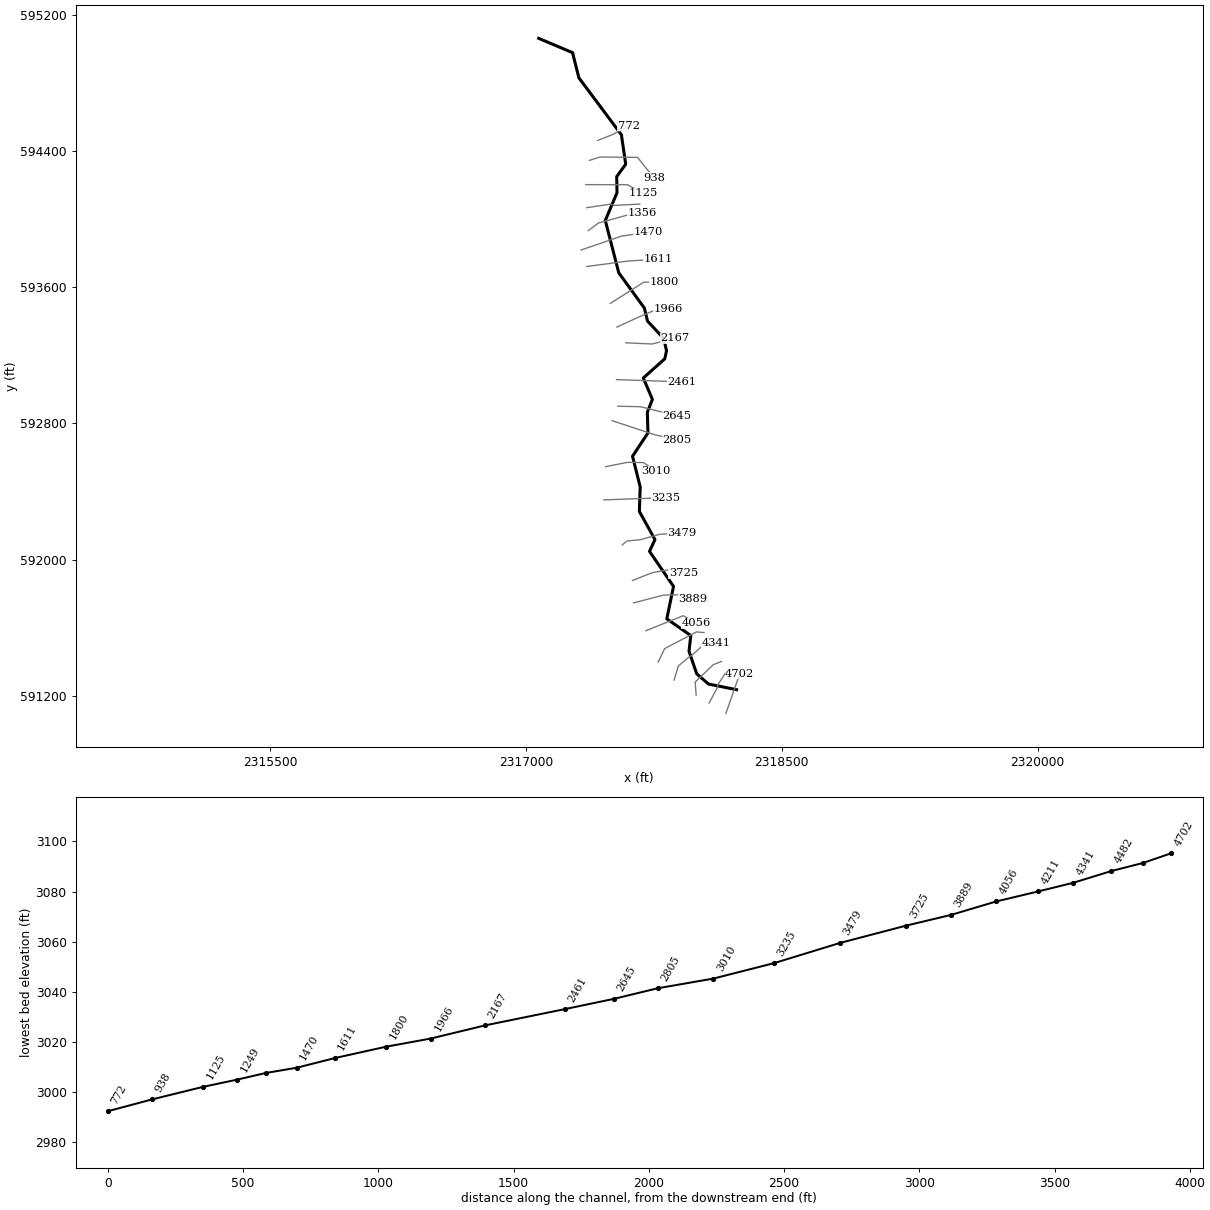
--- SPNOAKRN.prj (project) ---

Proj Title=SPNOAKRN
Current Plan=p01
Default Exp/Contr=0,0
English Units
Geom File=g01
Flow File=f01
Plan File=p01
Background Map Layer=Inundation Boundary (01pct Value_0)
Background Map Layer=Inundation Boundary (01pct Value_0)
Background Map Layer=Inundation Boundary (01pct Value_0)
BEGIN DESCRIPTION:
----------MODEL BY WOOD PLC 2021----------
Stream Name: Span Oak Run
Flood Zone: Enhanced Approximate
Pocahontas County, WV
HEC-RAS Version: RAS 6.1
Vertical Datum: NAVD88
Projection: NAD 1983 StatePlane West Virginia S FIPS 4702 (US Feet)
Terrain: 1-meter LIDAR (FEMA Region III 3DEP collected 2016-2018)
Land Use: 2019 NLCD
Hydrologic Method:
WV SIR2010-5033 regression equations
END DESCRIPTION:
DSS Export Rating Curves= 0
DSS Export Rating Curve Sorted= 0
DSS Export Volume Flow Curves= 0
DXF OffsetX= 0
DXF OffsetY= 0
DXF ScaleX= 0
DXF ScaleY= 0

--- SPNOAKRN.p01 (plan) ---

Plan Title=Floodplain
Program Version=6.10
Short Identifier=Floodplain
Geom File=g01
Flow File=f01
Subcritical Flow
K Sum by GR= 0
Std Step Tol= 0.01
Critical Tol= 0.01
Num of Std Step Trials= 20
Max Error Tol= 0.3
Flow Tol Ratio= 0.001
Split Flow NTrial= 30
Split Flow Tol= 0.02
Split Flow Ratio= 0.02
Log Output Level= 0
Friction Slope Method= 1
Unsteady Friction Slope Method= 2
Unsteady Bridges Friction Slope Method= 1
Parabolic Critical Depth
Global Vel Dist= 0 , 0 , 0
Global Log Level= 0
CheckData=True
Encroach Param=-1 ,0,0, 0
Mapping Interval=1HOUR
Computation Time Step Use Courant=        0
Computation Time Step Use Time Series=    0
Computation Time Step Count To Double=0
Computation Time Step Max Doubling=0
Computation Time Step Max Halving=0
Computation Time Step Residence Courant=0
Run HTab= 0
Run UNet= 0
Run Sediment= 0
Run PostProcess= 0
Run WQNet= 0
Run RASMapper=-1
UNET Theta= 0
UNET Theta Warmup= 0
UNET ZTol= 0
UNET ZSATol= 0
UNET MxIter= 0
UNET Max Iter WO Improvement= 0
UNET MaxInSteps= 0
UNET DtIC= 0
UNET DtMin= 0
UNET MaxCRTS= 0
UNET WFStab= 0
UNET SFStab= 0
UNET WFX= 1
UNET SFX= 1
UNET Gravity=32.174
UNET 1D Methodology=Finite Difference
UNET DSS MLevel= 1
UNET Pardiso=0
UNET DZMax Abort= 0
UNET Use Existing IB Tables= 0
UNET Froude Reduction=False
UNET Froude Limit= 0
UNET Froude Power= 0
UNET D1 Cores= 0
UNET WindReference=Eulerian
UNET WindDragFormulation=Hsu (1988)
UNET D2 Coriolis=0
UNET D2 Cores= 0
UNET D2 Theta= 1
UNET D2 Theta Warmup= 1
UNET D2 Z Tol= 0.01
UNET D2 Volume Tol= 0.01
UNET D2 Max Iterations= 20
UNET D2 Equation= 0
UNET D2 RampUpFraction=0.1
UNET D2 TimeSlices= 1
UNET D2 Turbulence Formulation=Non-Conservative (original)
UNET D2 Eddy Viscosity=0.3
UNET D2 Transverse Eddy Viscosity=0.1
UNET D2 Smagorinsky Mixing=0
UNET D2 BCVolumeCheck=0
UNET D2 Cores=0
UNET D2 SolverType=PARDISO (Direct)
UNET D2 Minimum Iterations= 2147483647
UNET D2 Maximum Iterations= 2147483647
UNET D2 Restart Number= 10
UNET D2 Relaxation Coeff=1.3
UNET D2 SOR Precondition Iterations= 10
UNET D2 ILUT Maximum Fill= 8
UNET D2 ILUT Tolerance=1E-08
UNET D1D2 MaxIter= 0
UNET D1D2 ZTol=0.01
UNET D1D2 QTol=0.1
UNET D1D2 MinQTol=1
Write IC File= 0
Write IC File at Fixed DateTime=0
Write IC File at Sim End=0
Echo Input=False
Echo Parameters=False
Echo Output=False
Write Detailed= 0
HDF Write Warmup=0
HDF Write Time Slices=0
HDF Flush=0
HDF Compression= 1
HDF Chunk Size= 1
HDF Spatial Parts= 1
HDF Use Max Rows=0
HDF Fixed Rows= 1
Calibration Method= 0
Calibration Iterations= 20
Calibration Max Change=0.05
Calibration Tolerance=0.2
Calibration Maximum=1.5
Calibration Minimum=0.5
Calibration Optimization Method= 1
WQ AD Non Conservative
WQ ULTIMATE=-1
WQ Max Comp Step=1HOUR
WQ Output Interval=15MIN
WQ Output Selected Increments= 0
WQ Output face flow=0
WQ Output face velocity=0
WQ Output face area=0
WQ Output face dispersion=0
WQ Output cell volume=0
WQ Output cell surface area=0
WQ Output cell continuity=0
WQ Output cumulative cell continuity=0
WQ Output face conc=0
WQ Output face dconc_dx=0
WQ Output face courant=0
WQ Output face peclet=0
WQ Output face adv mass=0
WQ Output face disp mass=0
WQ Output cell mass=0
WQ Output cell source sink temp=0
WQ Output nsm pathways=0
WQ Output nsm derived pathways=0
WQ Create Restart=0
WQ Fixed Restart=0
WQ System Summary=0
WQ Write To DSS=0
Sorting and Armoring Iterations= 10
XS Update Threshold= 0.02
Bed Roughness Predictor= 0
Hydraulics Update Threshold= 0.02
Energy Slope Method= 1
Volume Change Method= 1
Sediment Retention Method= 0
Sediment TS Multiplier= 1
Warm Up Method= 0
XS Weighting Method= 0
Number of US Weighted Cross Sections= 1
Number of DS Weighted Cross Sections= 1
Upstream XS Weight=0
Main XS Weight=1
Downstream XS Weight=0
Number of DS XS's Weighted with US Boundary= 1
Upstream Boundary Weight= 1
Weight of XSs Associated with US Boundary= 0
Number of US XS's Weighted with DS Boundary= 1
Downstream Boundary Weight= 0.5
Weight of XSs Associated with DS Boundary= 0.5
Percentile Method= 0
Sediment Output Level= 3
Mass or Volume Output= 0
Output Increment Type= 1
Profile and TS Output Increment= 1
Transport Output Increment 1
XS Output Flag= 0
XS Output Increment= 10
Read HDF5 Sediment Hotstart= 0
Sediment Hotstart Type= 0
Write Gradation File= 0
Read Gradation Hotstart= 0
Write HDF5 File= 1
Write Binary Output= 1
Write DSS Sediment File= 0
DSS Sediment Output Type= 1
SV Curve= 0
Specific Gage Flag= 0
Subcell Erosion Methods= 0
Subcell Deposition Methods= 0
Advection Scheme= 1
Matrix Solver= 0
Implicit Weighting Factor= 1
Maximum Outer Loop Convergence Iterations= 5
Convergence Maximum Absolute= 0.001
Convergence RMSE= 0.0001
Grain Fractions Max Abs Error= 0.001
Max Subgrid Regions= 1
Max Subgrid Length Scale= 3.402823E+38
Initial Layer Thickness= 3.402823E+38
Min Layer Thickness= 3.402823E+38
Max Layer Thickness= 3.402823E+38
Number of Layers= 5

--- SPNOAKRN.f01 (steady flow) ---

Flow Title=USGS Regression Equation
Program Version=6.10
Number of Profiles= 6
Profile Names=01pct,10pct,04pct,02pct,0_2pct,01plus
River Rch & RM=SPNOAKRN,Main,4702
     582     308     409     493     813     861
Boundary for River Rch & Prof#=SPNOAKRN,Main            , 1
Up Type= 0
Dn Type= 3
Dn Slope=0.03474
Boundary for River Rch & Prof#=SPNOAKRN,Main            , 2
Up Type= 0
Dn Type= 3
Dn Slope=0.03474
Boundary for River Rch & Prof#=SPNOAKRN,Main            , 3
Up Type= 0
Dn Type= 3
Dn Slope=0.03474
Boundary for River Rch & Prof#=SPNOAKRN,Main            , 4
Up Type= 0
Dn Type= 3
Dn Slope=0.03474
Boundary for River Rch & Prof#=SPNOAKRN,Main            , 5
Up Type= 0
Dn Type= 3
Dn Slope=0.03474
Boundary for River Rch & Prof#=SPNOAKRN,Main            , 6
Up Type= 0
Dn Type= 3
Dn Slope=0.03474
DSS Import GetInterval= 0
DSS Import GetPeak= 0
DSS Import FillOption= 0

--- SPNOAKRN.g01 (geometry) ---

Geom Title=Geometry
Program Version=6.10

River Reach=SPNOAKRN        ,Main
Reach XY= 30
2318234.83400004591235.9009999932318070.40100001591268.961999998
2318001.26586644591328.8728664222317956.05800003591461.682000011
2317966.46880734591553.9248423712317825.66723998591652.196429655
2317865.26199998591842.4570000022317724.44196165592048.504743711
2317756.28500003592117.6430000072317664.93899998592282.893000022
2317669.79700004592426.9829999952317624.85699998592607.130999997
2317715.20531304592744.3302804382317711.79466216592865.985453689
     2317741.448592941.106000006 2317688.0606958593066.835120246
2317814.09999999593179.7610000072317824.13100004593227.089000016
     2317807.889593298.7720000152317712.72713609593401.347271055
     2317694.402593477.4229999932317544.26807645593684.567226112
2317465.09100002593992.2140000022317533.83642645594155.322893426
2317532.09151973594249.816180661 2317584.8403406594322.734935477
2317559.55927175594495.6081013232317310.29304536594830.173236355
2317273.09257812594978.0315284282317074.53178465595062.211431418

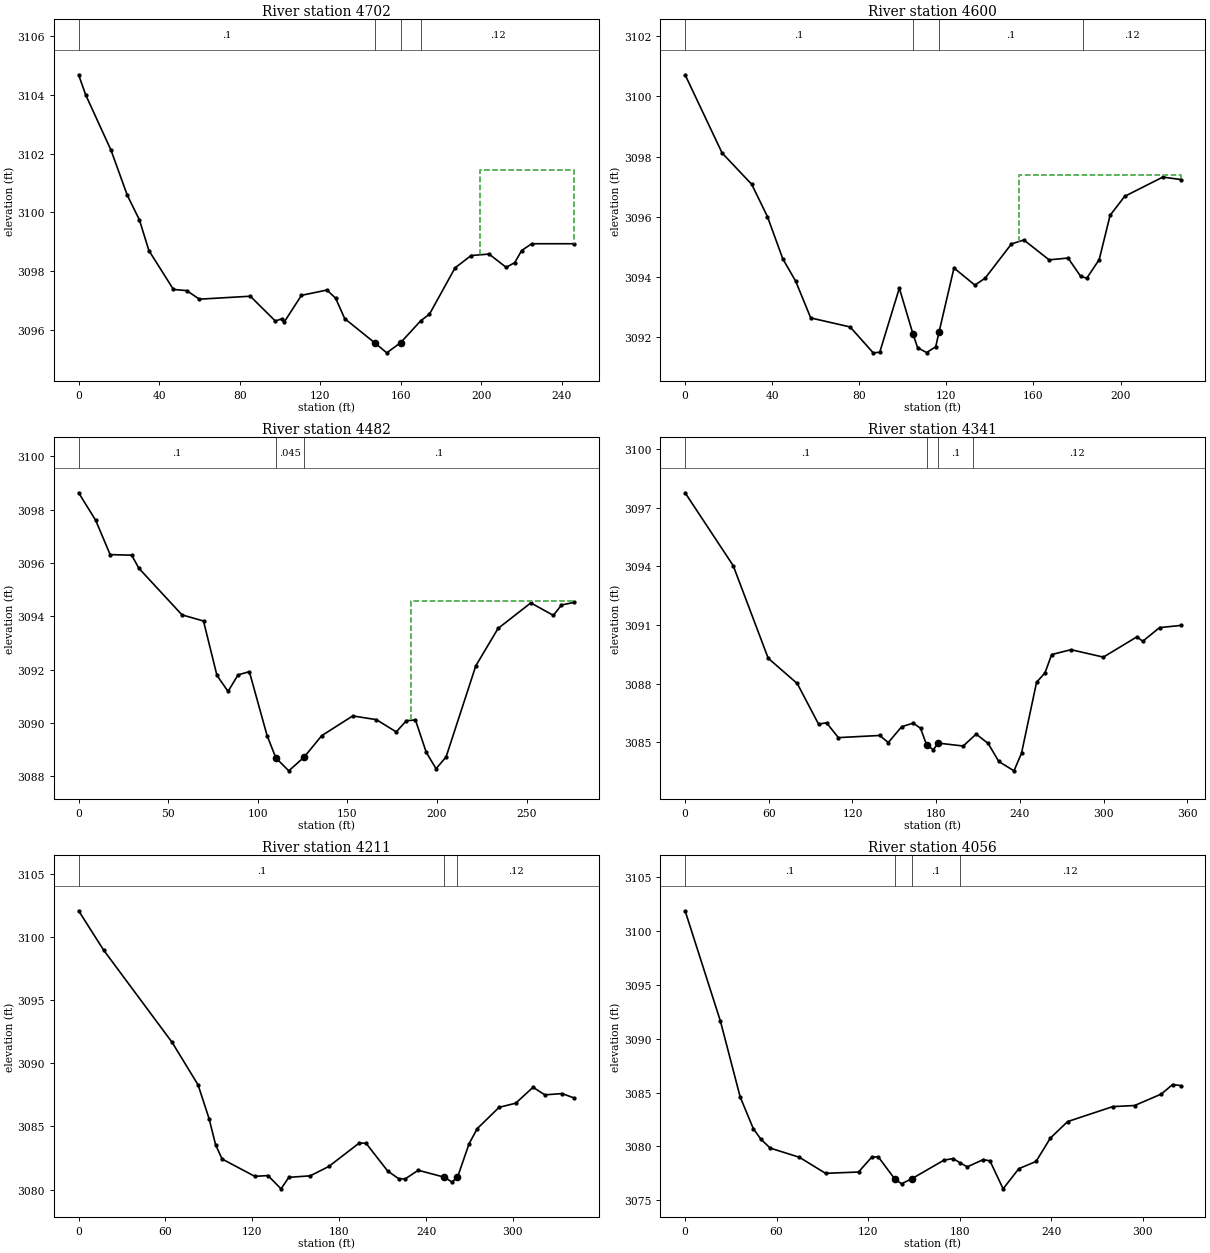
Type RM Length L Ch R = 1 ,4702    ,100.2,101,101.5
XS GIS Cut Line= 2
2318172.18406167591096.6839399332318253.48614244591329.023536264
#Sta/Elev= 30
       0 3104.67     3.5 3103.99    16.1 3102.11    24.2 3100.58    30.2 3099.75
    34.9 3098.71    47.1 3097.39    53.7 3097.35      60 3097.06    85.3 3097.16
    97.7 3096.32   100.8 3096.39   102.2 3096.29   110.7 3097.19   123.4 3097.37
   127.7 3097.09   132.2  3096.4     1473095.586   153.1 3095.24     1603095.586
     170 3096.33   174.3 3096.55     187 3098.12     195 3098.54   203.9 3098.59
   212.4 3098.14   216.7  3098.3   220.1 3098.71   225.1 3098.94   246.2 3098.94
#Mann= 4 ,-1,0
       0      .1       0     147    .045       0     160      .1       0
     170     .12       0
#XS Ineff= 2 , 0
                          199.55         3101.44
Permanent Ineff=
       F       F
Bank Sta=147,160
XS Rating Curve= 0 ,0
Exp/Cntr(USF)=0,0
Exp/Cntr=0.3,0.1

Type RM Length L Ch R = 1 ,4600    ,124.1,118.7,111.4
XS GIS Cut Line= 4
2318074.59823958591158.0906021412318120.64137639591245.684862414
2318127.37939641591268.7064308192318184.65256659591356.300691092
#Sta/Elev= 30
       0 3100.72      17 3098.12    30.6 3097.08    37.8 3096.01    44.9  3094.6
    50.8 3093.86    57.7 3092.64    75.8 3092.34    86.4 3091.48    89.4  3091.5
    98.4 3093.63   104.6 3092.12   106.8 3091.65   110.9 3091.49   115.1 3091.68
   116.6 3092.16   123.5  3094.3   133.1 3093.73   137.8 3093.96   149.9  3095.1
   155.6 3095.23   167.2 3094.57   175.9 3094.63   181.7 3094.02   184.5 3093.96
   190.2 3094.58   195.2 3096.05   201.9 3096.68   219.4 3097.32   227.6 3097.24
#Mann= 4 ,-1,0
       0      .1       0   104.6    .045       0   116.6      .1       0
  182.95     .12       0
#XS Ineff= 2 , 0
                          153.24         3097.38
Permanent Ineff=
       F       F
Bank Sta=104.6,116.6
XS Rating Curve= 0 ,0
Exp/Cntr(USF)=0,0
Exp/Cntr=0.3,0.1

Type RM Length L Ch R = 1 ,4482    ,143,140.4,135.2
XS GIS Cut Line= 4
2317997.96258502591203.6575835742317992.02523282591280.634480812
2318098.19177205591382.7379263892318146.81347095591401.541935484
#Sta/Elev= 30
       0 3098.63     9.5  3097.6    17.6 3096.31    29.6 3096.29    33.6  3095.8
    57.7 3094.05    69.7 3093.82    77.2 3091.78    83.4 3091.18      89  3091.8
    95.3 3091.92   105.2 3089.52   110.13088.685   117.3  3088.2   125.8 3088.71
   135.7 3089.52     153 3090.26   166.2 3090.12   177.3 3089.66   182.9 3090.08
     188 3090.11     194  3088.9   199.5 3088.28   205.1 3088.72   221.7 3092.14
   234.1 3093.54   252.4  3094.5     265 3094.03   269.5 3094.42   276.6 3094.52
#Mann= 3 ,-1,0
       0      .1       0   110.1    .045       0   125.8      .1       0
#XS Ineff= 2 , 0
                          185.54         3094.57
Permanent Ineff=
       F       F
Bank Sta=110.1,125.8
XS Rating Curve= 0 ,0
Exp/Cntr(USF)=0,0
Exp/Cntr=0.3,0.1

Type RM Length L Ch R = 1 ,4341    ,131,130.7,131.3
XS GIS Cut Line= 6
2317868.54336894591292.1171709142317893.33377562591374.944366396
 2317957.8860438591429.5400398362317971.79964726591436.496841563
2318042.23661779591500.6630855952318115.26316501591508.973728929
#Sta/Elev= 30
       0 3097.77    34.5 3094.04    59.6  3089.3    80.4 3088.01    95.7 3085.93
   101.4    3086   109.9 3085.24   139.5 3085.35   145.7 3084.99   155.3  3085.8
   163.5 3085.98   168.8 3085.72   173.2 3084.86     178 3084.62   181.4 3084.96
   199.4 3084.81   208.7 3085.42   217.3 3084.94   224.9 3084.02   235.8 3083.54
   241.2 3084.44     252 3088.07   258.1 3088.56   262.8 3089.49   276.7 3089.74
   299.9 3089.36     324  3090.4   328.1 3090.17   340.2 3090.87   355.3 3090.98
#Mann= 4 ,-1,0
       0      .1       0   173.2    .045       0   181.4      .1       0
  206.56     .12       0
Bank Sta=173.2,181.4
XS Rating Curve= 0 ,0
Exp/Cntr(USF)=0,0
Exp/Cntr=0.3,0.1

Type RM Length L Ch R = 1 ,4211    ,155.6,154.9,152.1
XS GIS Cut Line= 4
2317775.26999847 591399.104032282317813.53240797591477.368051709
2318000.06165427591575.1980759952318044.41126528591571.284875023
#Sta/Elev= 30
       0 3102.07    17.2 3098.97    64.6 3091.65    82.5 3088.29    90.1 3085.62
    94.6 3083.55    99.1 3082.42   121.7 3081.05   130.8 3081.11   139.8 3080.06
   145.2 3080.97     160 3081.09   172.8 3081.83     194  3083.7   198.6 3083.66
   213.4 3081.48   221.1 3080.86   225.6 3080.85   234.6 3081.53   252.7 3080.98
   257.8  3080.6   261.7 3080.97   269.7 3083.63   275.3 3084.82   290.4 3086.51
   301.9 3086.84   313.9  3088.1     322  3087.5     334  3087.6   342.3 3087.25
#Mann= 3 ,-1,0
       0      .1       0   252.7    .045       0   261.7     .12       0
Bank Sta=252.7,261.7
XS Rating Curve= 0 ,0
Exp/Cntr(USF)=0,0
Exp/Cntr=0.3,0.1

Type RM Length L Ch R = 1 ,4056    ,168.8,166.4,161.6
XS GIS Cut Line= 3
2317702.65838045591582.1548777222317922.66723506591670.419299633
2317998.75725395591626.504488731
#Sta/Elev= 30
       0 3101.87    23.2 3091.61    36.1  3084.6    44.7 3081.66    49.6 3080.69
    55.8 3079.85    74.9    3079    92.1 3077.51   113.7 3077.63   122.3    3079
   126.6 3079.05  137.323077.013   141.9 3076.54   148.63077.003   169.7 3078.73
   175.7 3078.88     180 3078.51     185 3078.11   195.6 3078.79   199.9 3078.66
   208.5 3076.07   218.8 3077.94   230.1 3078.61   239.5 3080.78   250.8 3082.31
   280.4  3083.7   294.7  3083.8   312.3 3084.87   319.6 3085.75   324.9 3085.65
#Mann= 4 ,-1,0
       0      .1       0  137.32    .045       0   148.6      .1       0
     180     .12       0
Bank Sta=137.32,148.6
XS Rating Curve= 0 ,0
Exp/Cntr(USF)=0,0
Exp/Cntr=0.3,0.1

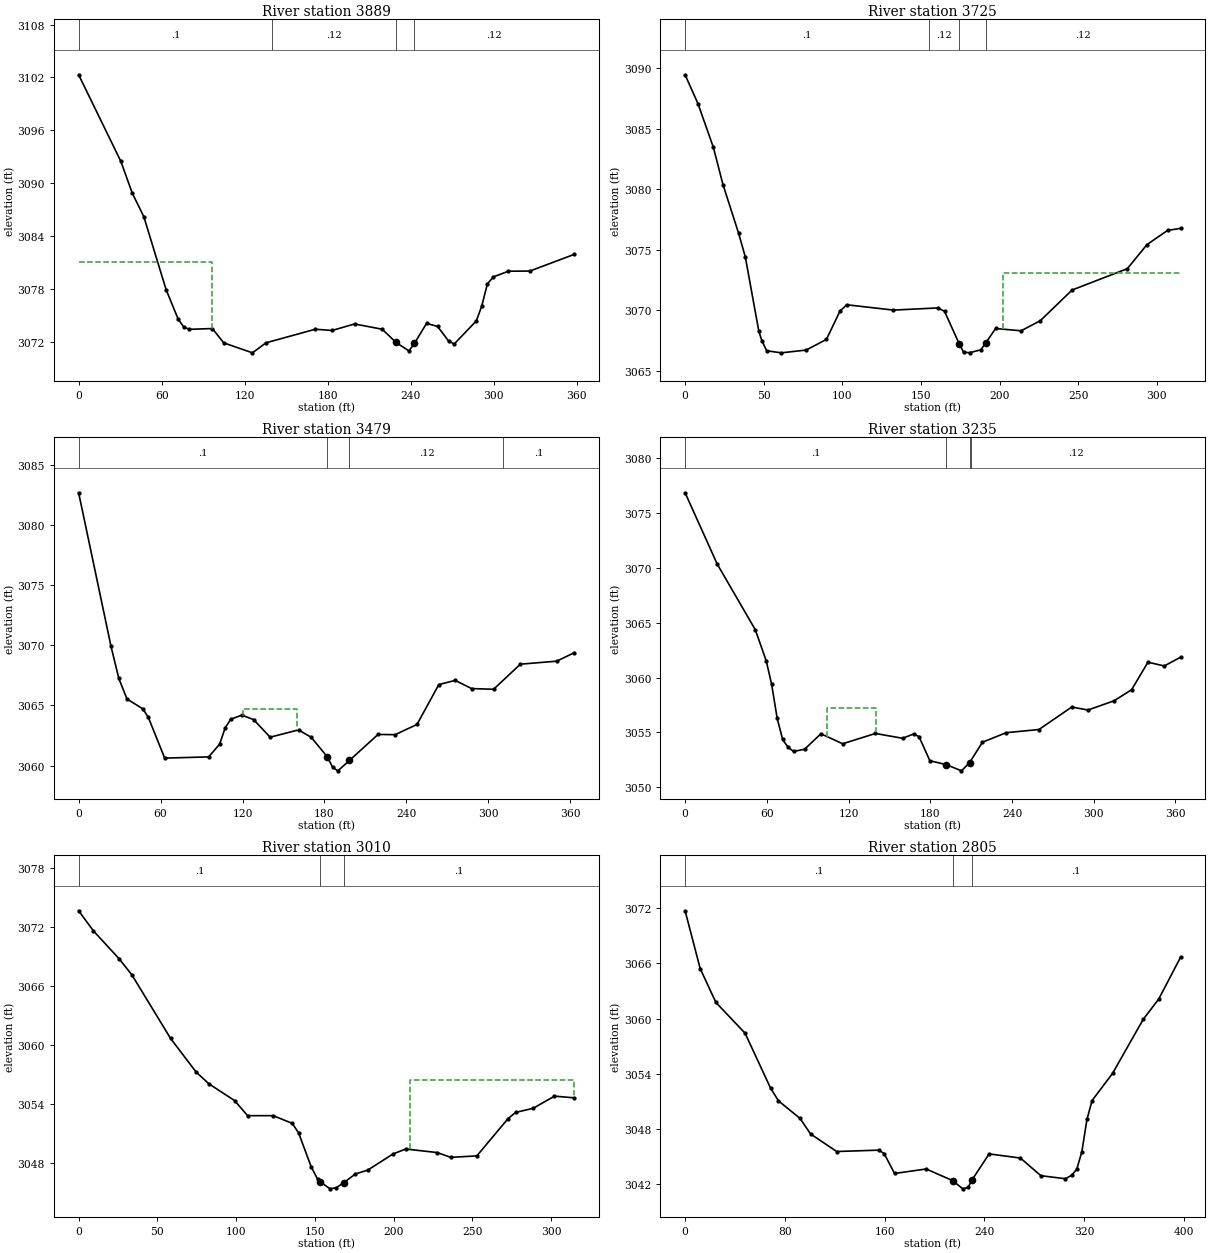
Type RM Length L Ch R = 1 ,3889    ,162.4,164.7,165
XS GIS Cut Line= 4
 2317630.6030654591745.7553703162317808.01728143591791.546931123
2317920.00153572591793.3630000812317977.38332757591767.788102185
#Sta/Elev= 30
       0  3102.3    30.5 3092.47    38.8 3088.84    47.1 3086.19    63.2  3077.9
    71.9 3074.56      76 3073.64    80.1 3073.39    96.6 3073.48   104.9 3071.85
   125.6 3070.72   135.4 3071.86     171  3073.4   183.2 3073.26   199.4    3074
   219.4  3073.4   229.33071.906   238.7 3070.94   242.7  3071.8   251.4 3074.06
   259.4 3073.72   267.4 3072.05   271.4 3071.72   287.4 3074.35   291.3 3076.03
   295.4 3078.56   299.8 3079.35   310.6 3079.99   326.1 3080.01   358.1  3081.9
#Mann= 4 ,-1,0
       0      .1       0     140     .12       0   229.3    .045       0
   242.7     .12       0
#XS Ineff= 2 , 0
           96.39 3081.02
Permanent Ineff=
       F       F
Bank Sta=229.3,242.7
XS Rating Curve= 0 ,0
Exp/Cntr(USF)=0,0
Exp/Cntr=0.3,0.1

Type RM Length L Ch R = 1 ,3725    ,241.6,245.4,245.1
XS GIS Cut Line= 4
2317624.54161491591877.497357964 2317741.2012592591923.443786069
2317865.43681415591945.5379337692317923.80767082591920.213678009
#Sta/Elev= 30
       0 3089.44     8.2 3087.05      18 3083.44    24.1 3080.37      34 3076.37
    38.3  3074.4    46.9 3068.26    48.8 3067.49    51.9 3066.65    61.2 3066.48
      77 3066.71    89.9 3067.59    98.5 3069.92   102.8 3070.45   132.5 3070.01
   160.9 3070.19     165 3069.91   174.3 3067.24   177.2 3066.51   181.3  3066.5
   188.1 3066.73   191.2 3067.29   197.5 3068.49   213.7  3068.3   225.9 3069.13
   246.2 3071.67   281.3 3073.43   293.8 3075.42   306.9 3076.59   315.2 3076.76
#Mann= 4 ,-1,0
       0      .1       0  155.38     .12       0   174.3    .045       0
   191.2     .12       0
#XS Ineff= 2 , 0
                          202.06         3073.06
Permanent Ineff=
       F       F
Bank Sta=174.3,191.2
XS Rating Curve= 0 ,0
Exp/Cntr(USF)=0,0
Exp/Cntr=0.3,0.1

Type RM Length L Ch R = 1 ,3479    ,247.7,244.1,241.3
XS GIS Cut Line= 5
2317564.91072507592087.1946843272317592.65395314592109.132608541
2317671.98376088592117.2646485152317783.53120052592148.699418363
2317915.18723741592155.628720756
#Sta/Elev= 30
       0 3082.71    23.7 3069.93    29.4 3067.26    35.4 3065.54      47 3064.72
      51 3064.02      63 3060.62    95.2 3060.72   103.2 3061.78   107.3 3063.14
   111.3 3063.85   119.5  3064.2   128.2 3063.82   140.2 3062.36     161 3062.97
   170.3 3062.35     1823060.735     186 3059.85   189.8 3059.56   198.33060.427
   219.2 3062.59   231.7 3062.57   247.7 3063.42   263.7 3066.74   275.7 3067.09
   287.7 3066.41   303.8 3066.35   323.4 3068.44     350 3068.69   362.8 3069.39
#Mann= 4 ,-1,0
       0      .1       0     182    .045       0   198.3     .12       0
  311.01      .1       0
#XS Ineff= 1 ,-1
  120.34  159.55 3064.69
Permanent Ineff=
       F
Bank Sta=182,198.3
XS Rating Curve= 0 ,0
Exp/Cntr(USF)=0,0
Exp/Cntr=0.3,0.1

Type RM Length L Ch R = 1 ,3235    ,223.8,224.7,223
XS GIS Cut Line= 2
2317456.57926868592350.7239614432317820.10179559592363.821922445
#Sta/Elev= 30
       0 3076.86    23.6 3070.35    51.6 3064.35    59.6 3061.51    63.5  3059.4
    67.6 3056.28    71.6 3054.35    75.6 3053.64    79.6 3053.26    87.7 3053.46
    99.7 3054.87   115.7 3053.96   139.7  3054.9   159.7 3054.46   167.7 3054.85
   171.7 3054.62   179.7 3052.41   191.7 3052.06   202.9 3051.49   208.8 3052.23
   218.3  3054.1   235.7 3054.97   259.8 3055.26   283.8 3057.31   295.8 3057.04
   314.9 3057.88   327.8 3058.89   339.8  3061.4   351.8 3061.06   363.8 3061.86
#Mann= 4 ,-1,0
       0      .1       0   191.7    .045       0   208.8      .1       0
     210     .12       0
#XS Ineff= 1 ,-1
  104.32   140.23057.244
Permanent Ineff=
       F
Bank Sta=191.7,208.8
XS Rating Curve= 0 ,0
Exp/Cntr(USF)=0,0
Exp/Cntr=0.3,0.1

Type RM Length L Ch R = 1 ,3010    ,208.4,205.8,201
XS GIS Cut Line= 4
2317467.00465881592545.7637855392317594.20358046592571.367576098
2317690.04083132592569.9756902752317762.36402439592517.877336708
#Sta/Elev= 30
       0 3073.68     9.4 3071.63    25.7 3068.79    33.8 3067.15    58.4 3060.66
    74.6 3057.24    82.8 3056.03    99.1 3054.32   107.3 3052.79   123.6 3052.79
   135.7    3052   139.7 3051.03   147.7 3047.57   151.7 3046.33   153.6 3046.02
   159.7 3045.33   163.7 3045.45   168.43045.962   175.7 3046.84   183.7 3047.25
   199.7 3048.89   207.7 3049.39   227.7 3049.03   236.3 3048.54   252.9 3048.69
   272.6 3052.47   277.5 3053.12   288.6 3053.54   302.2 3054.78   314.7 3054.61
#Mann= 3 ,-1,0
       0      .1       0   153.6    .045       0   168.4      .1       0
#XS Ineff= 2 , 0
                          210.39         3056.38
Permanent Ineff=
       F       F
Bank Sta=153.6,168.4
XS Rating Curve= 0 ,0
Exp/Cntr(USF)=0,0
Exp/Cntr=0.3,0.1

Type RM Length L Ch R = 1 ,2805    ,155.4,159.7,158.3
XS GIS Cut Line= 3
2317504.67518611592816.2648479252317754.29370055592733.795014246
2317885.36182908592703.605164417
#Sta/Elev= 30
       0 3071.72    12.1 3065.43    24.7 3061.75    48.1  3058.4    68.5 3052.44
    74.9 3051.04    92.2 3049.13   100.6 3047.44   121.6 3045.53   155.3 3045.68
   159.6 3045.31     168 3043.14   193.3 3043.63   214.5 3042.37   222.7 3041.47
     227 3041.63     230 3042.42   243.8 3045.27   268.9 3044.82   285.3  3042.9
     305 3042.57     310 3042.95   314.1  3043.6   318.2 3045.53   322.3 3049.04
   326.4 3051.08   342.8 3054.03   367.4 3059.91   379.8 3062.11   397.4 3066.68
#Mann= 3 ,-1,0
       0      .1       0   214.5    .045       0     230      .1       0
Bank Sta=214.5,230
XS Rating Curve= 0 ,0
Exp/Cntr(USF)=0,0
Exp/Cntr=0.3,0.1

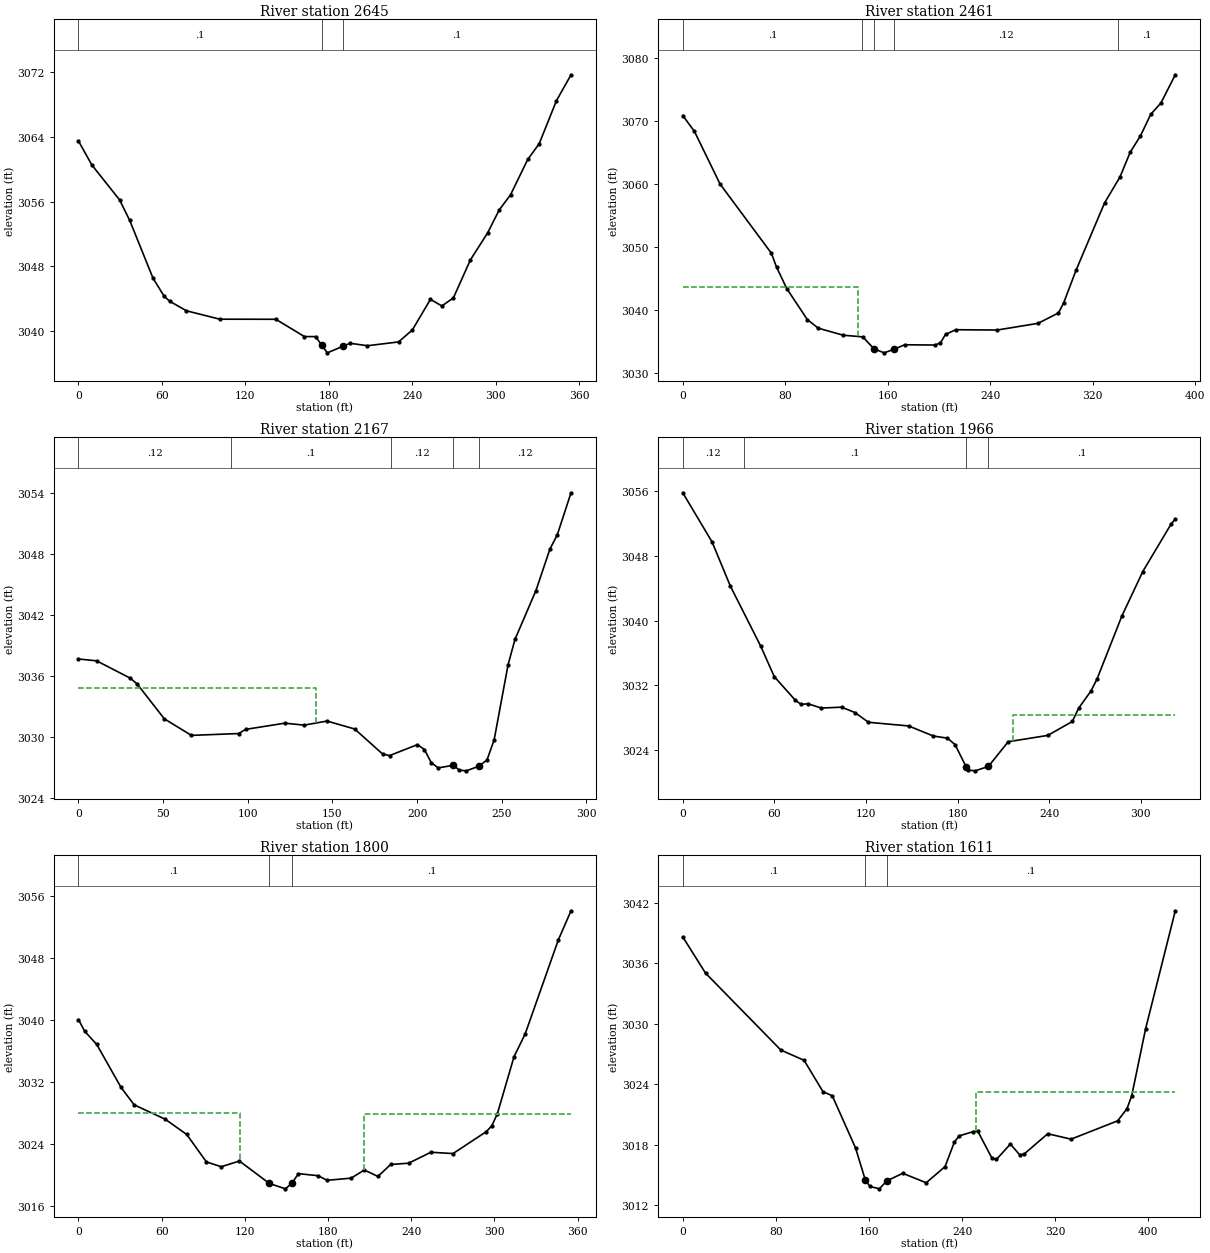
Type RM Length L Ch R = 1 ,2645    ,181.4,184.2,186.3
XS GIS Cut Line= 3
2317538.60395512592901.1590371532317670.55528713592898.288897895
2317886.42724333592845.360357455
#Sta/Elev= 30
       0 3063.49     9.6 3060.53    29.6  3056.2    36.8 3053.69    53.6 3046.53
    61.6  3044.3    65.6 3043.68    77.6  3042.5   101.6 3041.46   141.9 3041.45
   162.5 3039.31   170.6 3039.31   174.8 3038.26     179  3037.3   190.5 3038.14
   195.4 3038.48   207.8 3038.18   230.2 3038.65   240.1 3040.13   253.1 3043.91
   261.3  3043.1   269.6 3044.09   281.9 3048.81   294.3 3052.15   302.5 3054.95
   310.7 3056.84   323.1 3061.22   331.3 3063.15   343.7 3068.47   354.2 3071.68
#Mann= 3 ,-1,0
       0      .1       0   174.8    .045       0   190.5      .1       0
Bank Sta=174.8,190.5
XS Rating Curve= 0 ,0
Exp/Cntr(USF)=0,0
Exp/Cntr=0.3,0.1

Type RM Length L Ch R = 1 ,2461    ,288.6,294,295.4
XS GIS Cut Line= 2
2317531.06099755593057.3400725052317915.31295403593044.282967188
#Sta/Elev= 30
       0 3070.81     9.1  3068.3    29.1 3059.94    69.2 3048.95    73.2 3046.75
    81.2 3043.34    97.2 3038.43   105.7 3037.06   125.2 3035.94   140.6 3035.67
   149.2 3033.79   157.2 3033.14   165.2 3033.73   173.2 3034.42   197.2 3034.38
   201.2 3034.76   205.2 3036.08   213.2 3036.81   245.4 3036.76   277.3 3037.82
   293.3 3039.47   297.3 3041.04     307 3046.24   329.3 3056.95   341.3 3061.05
   349.3 3064.98   357.3 3067.58   365.3 3070.99   373.3 3072.81   384.5 3077.28
#Mann= 5 ,-1,0
       0      .1       0     140     .12       0   149.2    .045       0
   165.2     .12       0     340      .1       0
#XS Ineff= 2 , 0
          137.01 3043.57
Permanent Ineff=
       F       F
Bank Sta=149.2,165.2
XS Rating Curve= 0 ,0
Exp/Cntr(USF)=0,0
Exp/Cntr=0.3,0.1

Type RM Length L Ch R = 1 ,2167    ,196.4,200.3,200.7
XS GIS Cut Line= 3
2317585.50196458 593273.515854462317739.77393288593266.701147328
2317872.33040063593299.366312435
#Sta/Elev= 30
       0 3037.68    10.7  3037.5    30.7 3035.78    34.7 3035.21    50.7 3031.79
    66.7 3030.16    94.6 3030.34    98.7 3030.75   121.8 3031.36   133.3 3031.17
   146.8 3031.57   163.1 3030.79   179.6 3028.33   183.7 3028.17   200.2 3029.25
   204.3 3028.77   208.4 3027.46   212.5 3026.96   221.43027.216   224.9 3026.74
     229 3026.67   236.53027.128   241.3 3027.75   245.5 3029.72   253.7 3037.09
   257.8 3039.61   270.2 3044.42   278.4 3048.48   282.8 3049.91   290.9 3054.04
#Mann= 5 ,-1,0
       0     .12       0      90      .1       0  184.42     .12       0
   221.4    .045       0   236.5     .12       0
#XS Ineff= 2 , 0
          140.22 3034.81
Permanent Ineff=
       F       F
Bank Sta=221.4,236.5
XS Rating Curve= 0 ,0
Exp/Cntr(USF)=0,0
Exp/Cntr=0.3,0.1

Type RM Length L Ch R = 1 ,1966    ,164.7,166.3,168.5
XS GIS Cut Line= 4
2317533.82929766593366.0401409232317657.04267198593423.076374897
 2317748.6322955593462.2830716652317834.81841482593474.588042361
#Sta/Elev= 30
       0 3055.81    19.2 3049.73    31.2 3044.26    51.1 3036.83    59.9 3033.09
    73.4 3030.23    77.5 3029.64    81.9 3029.74    90.7  3029.2     104 3029.31
   112.8 3028.64   121.6 3027.44   147.9 3026.99   164.1 3025.74   173.3 3025.48
   178.3 3024.68   185.5 3021.96     187 3021.53   191.4 3021.44   200.1 3021.98
   213.1 3025.04     239 3025.82   255.1 3027.54   259.2 3029.18   267.3 3031.31
   271.3 3032.81   287.5 3040.57   301.2 3046.07   319.8 3051.96   322.5 3052.57
#Mann= 4 ,-1,0
       0     .12       0      40      .1       0   185.5    .045       0
   200.1      .1       0
#XS Ineff= 2 , 0
                          216.11         3028.33
Permanent Ineff=
       F       F
Bank Sta=185.5,200.1
XS Rating Curve= 0 ,0
Exp/Cntr(USF)=0,0
Exp/Cntr=0.3,0.1

Type RM Length L Ch R = 1 ,1800    ,195.1,188.8,182.6
XS GIS Cut Line= 3
2317494.31501948593504.7856692972317689.70243494593629.346987775
2317813.17179435 593633.63146401
#Sta/Elev= 30
       0    3040     4.5 3038.48    13.2 3036.78    30.7 3031.24    40.2 3028.99
    62.5 3027.15    78.1 3025.17    92.3 3021.63     103 3021.01   116.1 3021.75
   137.73018.854   149.3 3018.16     154  3018.9   158.7 3020.12     173 3019.85
   179.3 3019.26   196.7 3019.54   206.2 3020.59     216 3019.76   225.2  3021.3
   238.2 3021.47   254.2 3022.88   270.2 3022.71   294.2 3025.54   298.2  3026.3
   302.2 3027.87   314.2 3035.21   322.2 3038.13   346.1 3050.25   355.3 3054.03
#Mann= 3 ,-1,0
       0      .1       0   137.7    .045       0     154      .1       0
#XS Ineff= 2 , 0
          116.87  3027.9  205.97         3027.86
Permanent Ineff=
       F       F
Bank Sta=137.7,154
XS Rating Curve= 0 ,0
Exp/Cntr(USF)=0,0
Exp/Cntr=0.3,0.1

Type RM Length L Ch R = 1 ,1611    ,137.2,141.2,144.2
XS GIS Cut Line= 3
2317356.74703501593721.9474793122317604.23140919593754.582781401
2317777.60645153593764.101411177
#Sta/Elev= 30
       0  3038.6    19.6 3035.01    84.2  3027.4   104.3 3026.37   120.5 3023.27
   128.5 3022.86   148.5 3017.69   156.8 3014.55   160.8 3013.88   168.9 3013.64
  175.54 3014.44   189.1 3015.18   209.2 3014.24   225.4 3015.84   233.4 3018.26
   237.5 3018.88   249.6 3019.31   253.6 3019.34   265.6 3016.71   269.6 3016.56
   281.6 3018.08   289.6    3017   293.4 3017.09   313.7  3019.1   333.7 3018.56
   373.8 3020.38   381.8 3021.59   385.8 3022.84   397.8 3029.51   423.3 3041.19
#Mann= 3 ,-1,0
       0      .1       0   156.8    .045       0  175.54      .1       0
#XS Ineff= 2 , 0
                          251.66         3023.23
Permanent Ineff=
       F       F
Bank Sta=156.8,175.54
XS Rating Curve= 0 ,0
Exp/Cntr(USF)=0,0
Exp/Cntr=0.3,0.1

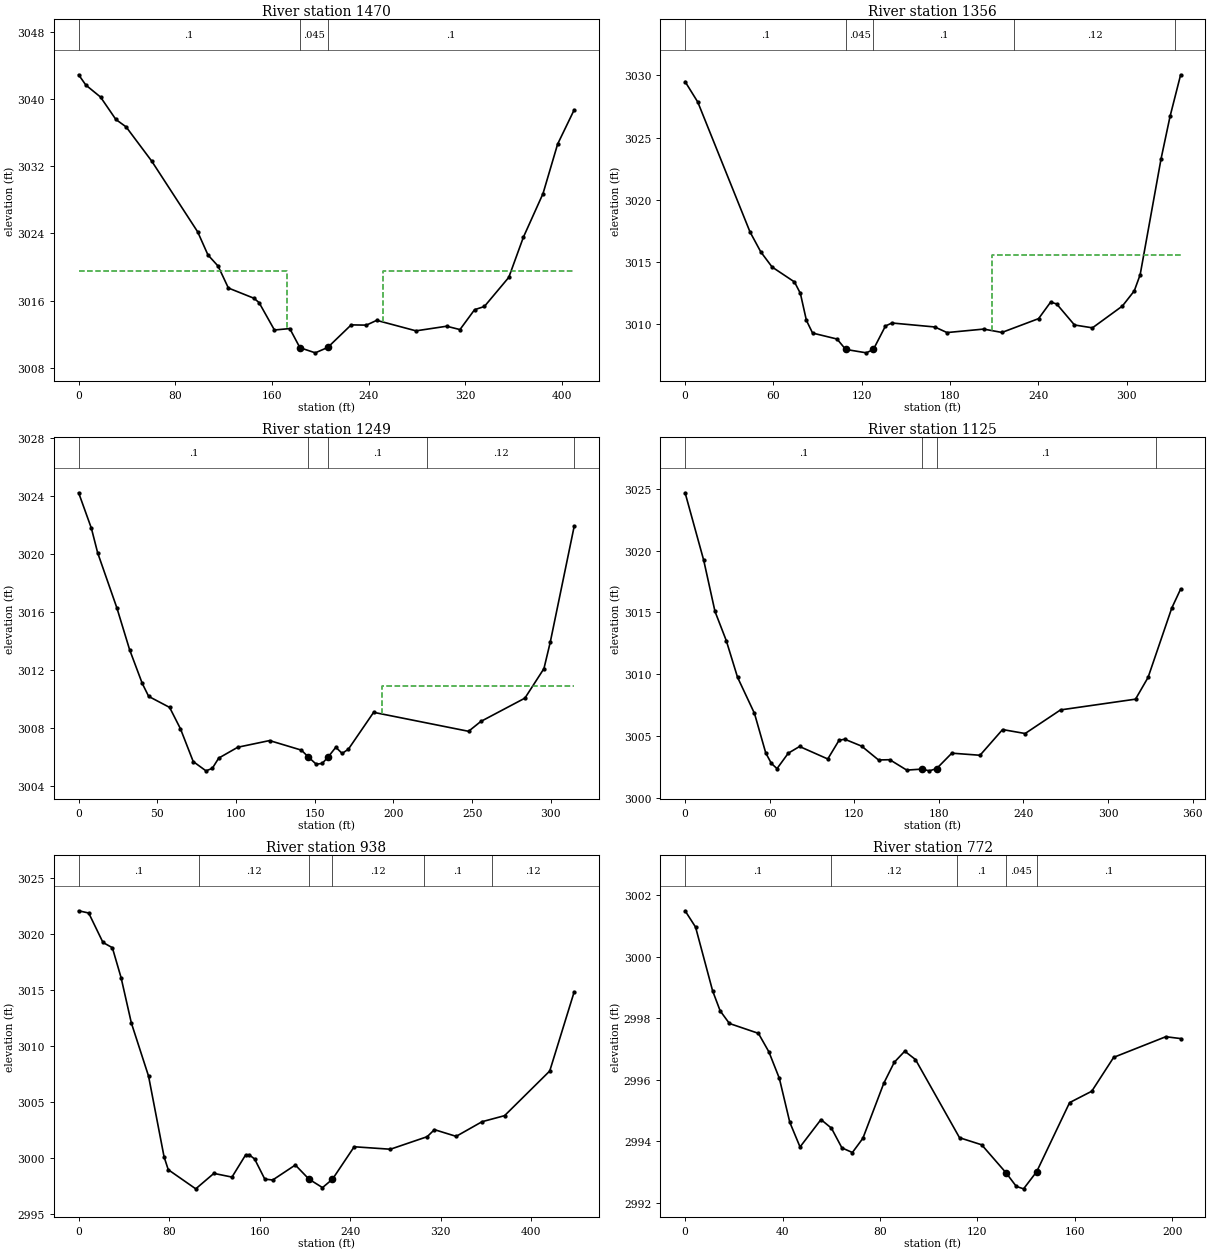
Type RM Length L Ch R = 1 ,1470    ,115.1,114.4,113.4
XS GIS Cut Line= 3
2317323.02904669593818.6705672052317560.12981852593900.404063083
2317717.70610787593923.230534905
#Sta/Elev= 30
       0  3042.9       6 3041.67    18.1 3040.25    30.8 3037.58    39.3 3036.69
    60.4 3032.63    98.5 3024.19     107 3021.44   115.4 3020.11   123.9  3017.5
   145.1 3016.28   149.3 3015.76     162  3012.5   174.7 3012.67   183.1 3010.39
   195.8 3009.78   206.13010.421   225.5 3013.11   238.1 3013.08   246.6 3013.65
   279.1  3012.4   304.5 3012.95   315.5 3012.55   327.6 3014.92   335.7  3015.3
   355.9 3018.77     368 3023.56   384.2 3028.74   396.3 3034.64     410 3038.72
#Mann= 3 ,-1,0
       0      .1       0   183.1    .045       0   206.1      .1       0
#XS Ineff= 2 , 0
           172.8 3019.47  251.55         3019.47
Permanent Ineff=
       F       F
Bank Sta=183.1,206.1
XS Rating Curve= 0 ,0
Exp/Cntr(USF)=0,0
Exp/Cntr=0.3,0.1

Type RM Length L Ch R = 1 ,1356    ,114,106.3,95.9
XS GIS Cut Line= 4
2317365.10338862593932.2064926952317423.76742121593976.806473284
2317586.71161312594021.8998001992317679.23982116594037.362894013
#Sta/Elev= 30
       0  3029.5     8.6 3027.86    44.1 3017.41    51.4 3015.81    59.1 3014.59
    74.3 3013.39    78.3 3012.47    82.4  3010.3    86.6 3009.28   103.2  3008.8
  109.073007.966   123.1 3007.69   127.93007.964   136.1 3009.85   140.5 3010.09
   169.6 3009.77   177.9 3009.32   202.8  3009.6   215.2 3009.33   240.1 3010.44
   248.3 3011.77   252.4 3011.62   264.5 3009.93   276.7  3009.7     297 3011.45
   305.1 3012.67   309.1 3013.97   323.3 3023.29   329.4  3026.7   336.6 3030.05
#Mann= 5 ,-1,0
       0      .1       0  109.07    .045       0   127.9      .1       0
  223.69     .12       0  332.76      .1       0
#XS Ineff= 2 , 0
                          208.14         3015.58
Permanent Ineff=
       F       F
Bank Sta=109.07,127.9
XS Rating Curve= 0 ,0
Exp/Cntr(USF)=0,0
Exp/Cntr=0.3,0.1

Type RM Length L Ch R = 1 ,1249    ,120.8,124.6,127.8
XS GIS Cut Line= 4
2317356.16424772594067.5527438422317498.08241632594088.467628443
2317514.24784953594080.5433964762317667.34401114594088.467628443
#Sta/Elev= 30
       0 3024.23     8.1 3021.78    12.1 3020.08    24.3 3016.28    32.4 3013.39
    40.4 3011.07    44.5 3010.17    57.8 3009.41    64.7 3007.93    72.8 3005.67
    80.9 3005.03    84.9  3005.2      89 3005.91   101.1 3006.66   121.3 3007.12
   141.5 3006.46   145.8    3006   150.9 3005.49   154.7 3005.54   158.3 3005.96
   163.4 3006.66   167.4 3006.23   171.4 3006.53   187.4 3009.07   247.7 3007.76
   255.5 3008.44   283.5 3010.05   295.6 3012.09   299.6 3013.91   314.8 3021.91
#Mann= 5 ,-1,0
       0      .1       0   145.8    .045       0   158.3      .1       0
  221.45     .12       0  314.76      .1       0
#XS Ineff= 2 , 0
                          192.44          3010.9
Permanent Ineff=
       F       F
Bank Sta=145.8,158.3
XS Rating Curve= 0 ,0
Exp/Cntr(USF)=0,0
Exp/Cntr=0.3,0.1

Type RM Length L Ch R = 1 ,1125    ,181.6,187.4,189.1
XS GIS Cut Line= 3
2317350.96671608594202.8086428812317594.90806608594202.212209262
2317689.74101143594151.515351683
#Sta/Elev= 30
       0 3024.68    13.2 3019.22    21.2 3015.08    29.2 3012.72    37.2 3009.75
    49.2 3006.83    57.2 3003.63    61.2 3002.78    65.2 3002.36    73.2 3003.61
    81.2 3004.15   101.2 3003.14   109.2 3004.65   113.2 3004.74   125.2 3004.18
   137.2 3003.06   145.2 3003.08   157.2 3002.24     168 3002.32   173.2 3002.18
   178.4 3002.36   189.2 3003.61   209.2 3003.44   225.2 3005.52   241.2  3005.2
   266.3 3007.11   319.5 3007.98   328.4 3009.74   345.2 3015.35   351.5 3016.89
#Mann= 4 ,-1,0
       0      .1       0     168    .045       0   178.4      .1       0
  333.94     .12       0
Bank Sta=168,178.4
XS Rating Curve= 0 ,0
Exp/Cntr(USF)=0,0
Exp/Cntr=0.3,0.1

Type RM Length L Ch R = 1 ,938     ,156.6,165.2,170.1
XS GIS Cut Line= 4
2317371.68016512594345.336218396 2317435.0638563594365.038587131
  2317654.124066594363.0209890062317749.27905746594243.851921023
#Sta/Elev= 30
       0 3022.06     8.9 3021.86    21.5 3019.23    29.8 3018.76    37.5 3016.09
    46.6 3012.03    61.8 3007.28    75.5 3000.07    79.2 2998.92   103.5 2997.21
   119.5 2998.59   135.5 2998.26   147.5 3000.23   150.6 3000.26   155.5 2999.88
   164.5 2998.08   171.5    2998   191.5 2999.34   203.5 2998.08   215.5 2997.32
   224.3 2998.07   243.5 3000.97   275.5 3000.75     308 3001.87   314.4  3002.5
   333.6  3001.9   356.5 3003.21   376.4 3003.75   416.3 3007.74   437.9 3014.81
#Mann= 6 ,-1,0
       0      .1       0  106.38     .12       0   203.5    .045       0
   224.3     .12       0  305.44      .1       0  365.44     .12       0
Bank Sta=203.5,224.3
XS Rating Curve= 0 ,0
Exp/Cntr(USF)=0,0
Exp/Cntr=0.3,0.1

Type RM Length L Ch R = 1 ,772     ,141.3,142.2,142.7
XS GIS Cut Line= 3
2317420.14394672594462.5883167762317505.47574259594495.799304591
 2317604.4697185594548.003709135
#Sta/Elev= 30
       0 3001.49     4.3 3000.96    11.3 2998.89    14.4 2998.24    18.2 2997.83
    30.1 2997.51    34.4 2996.91    38.7 2996.05      43 2994.62    47.2 2993.82
    55.8 2994.71    60.1 2994.43    64.4 2993.79    68.7 2993.64      73  2994.1
    81.6 2995.89    85.9 2996.57    90.2 2996.93    94.6 2996.66   112.7 2994.12
   121.8 2993.89   131.82992.981     136 2992.54     139 2992.46   144.4 2993.02
   157.9 2995.26     167 2995.63     176 2996.73   197.4  2997.4   203.5 2997.34
#Mann= 5 ,-1,0
       0      .1       0      60     .12       0  111.57      .1       0
   131.8    .045       0   144.4      .1       0
Bank Sta=131.8,144.4
XS Rating Curve= 0 ,0
Exp/Cntr(USF)=0,0
Exp/Cntr=0.3,0.1