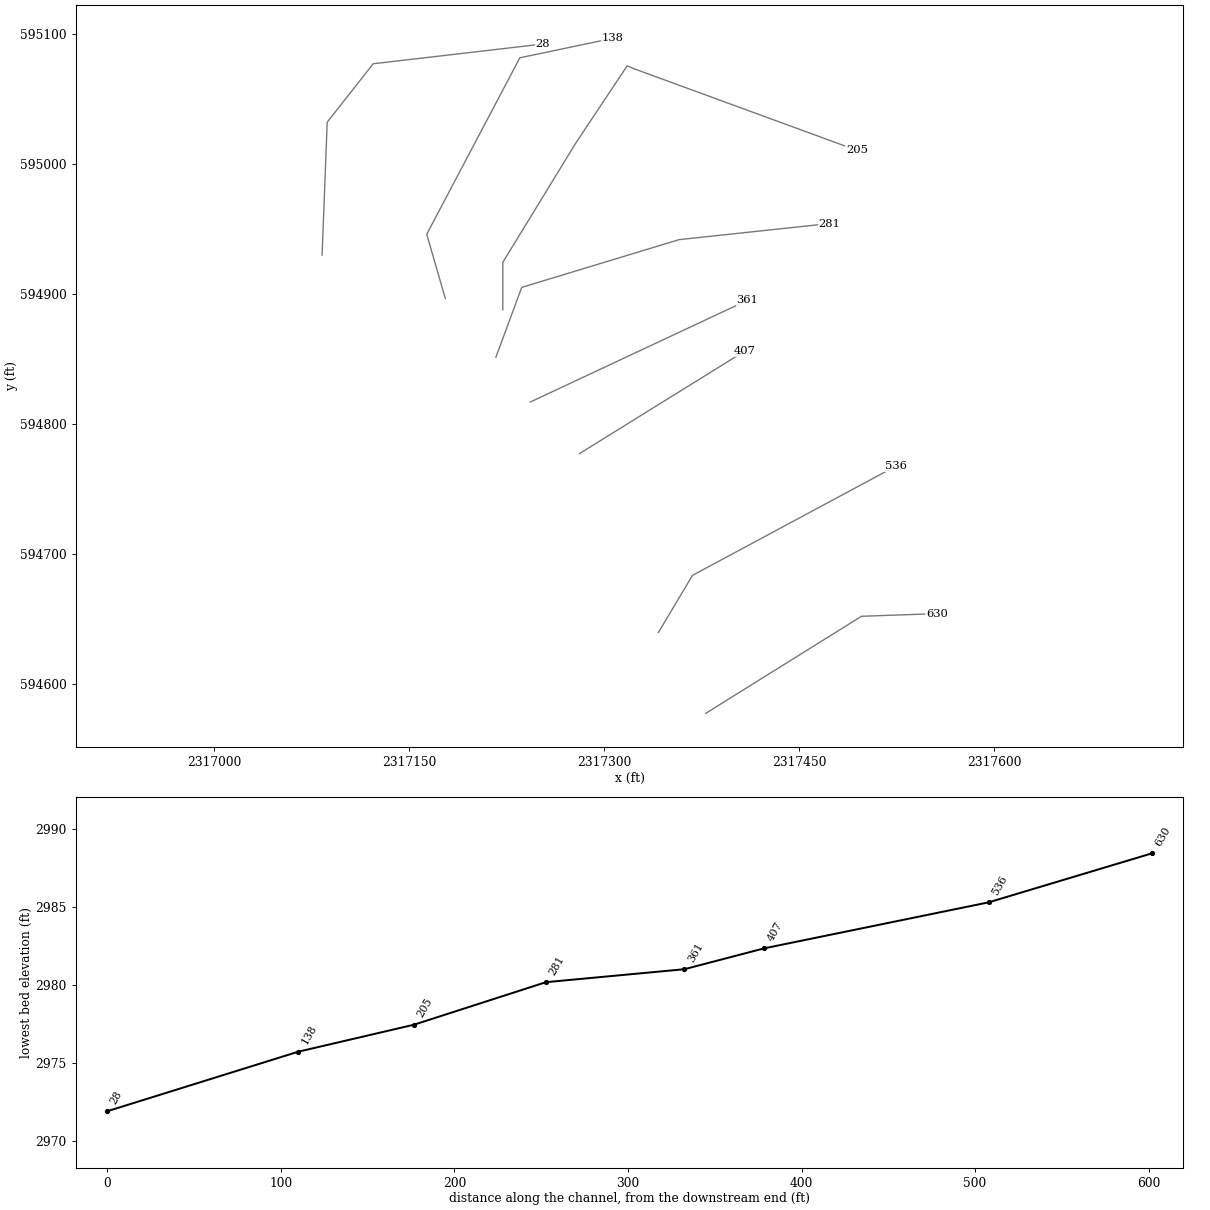
HEC-RAS study SPNOAKRN.prj: SPNOAKRN

--- SPNOAKRN.g01 (geometry) --- (continued)

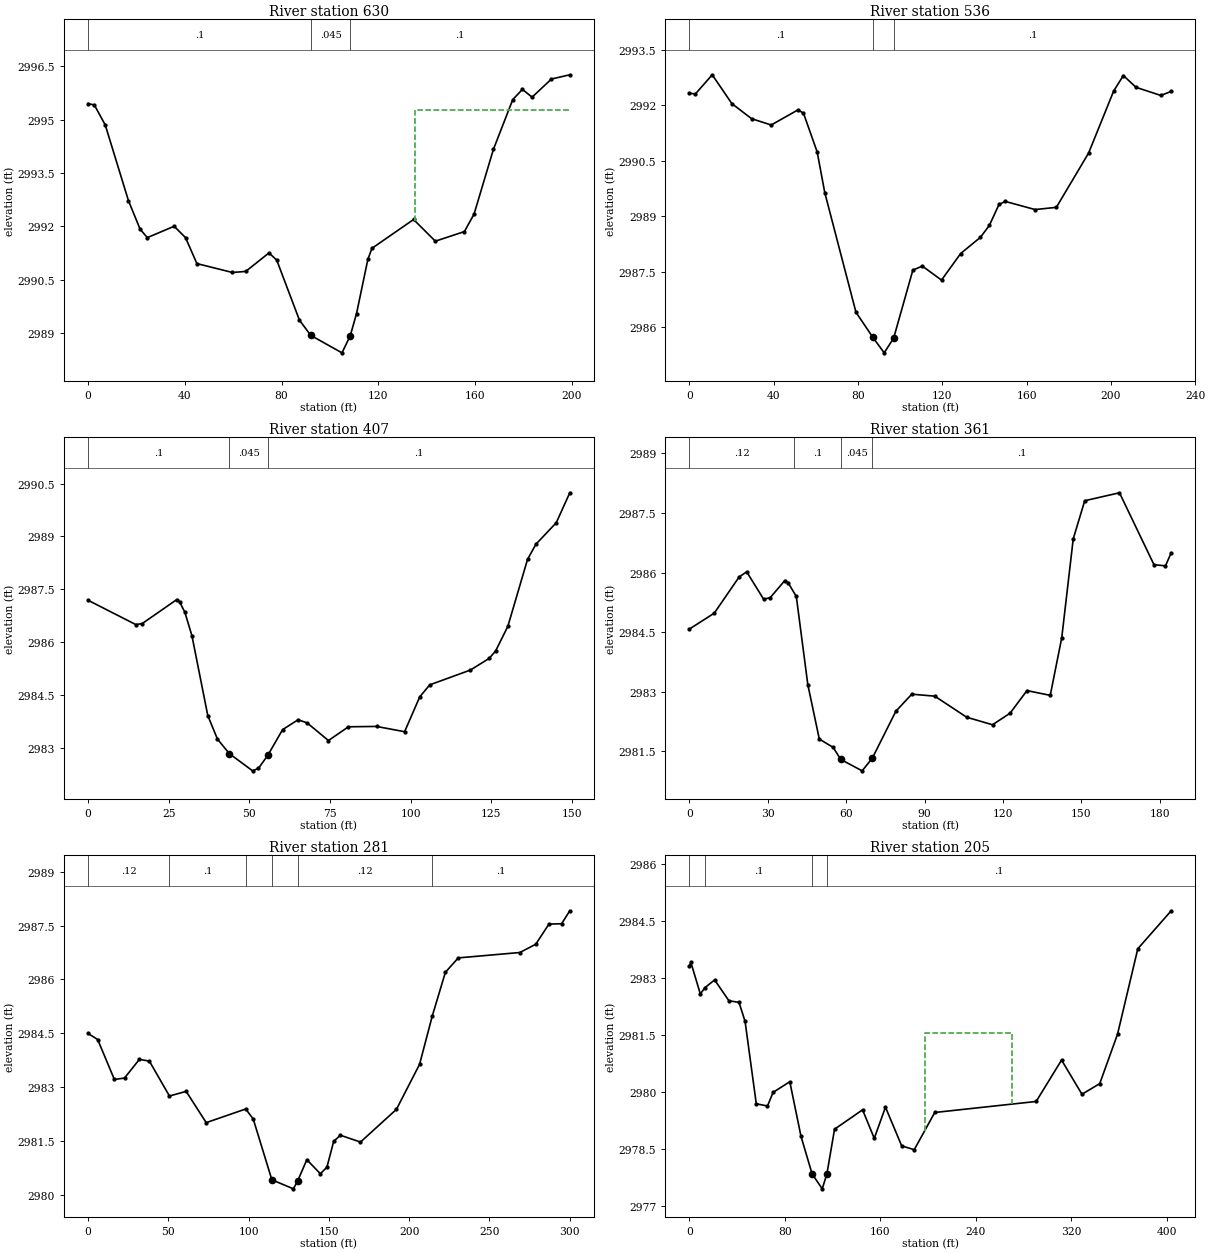
Type RM Length L Ch R = 1 ,630     ,94.2,94,93.9
XS GIS Cut Line= 3
2317377.95939359594577.6361052742317497.82086617594652.301360986
2317555.81708301594654.354795401
#Sta/Elev= 30
       0 2995.45     2.6 2995.41     7.1 2994.85    16.7 2992.72    21.5 2991.92
    24.5 2991.68    35.6    2992    40.3 2991.68      45 2990.95    59.7  2990.7
    65.2 2990.73    74.8 2991.25      78 2991.05    87.4 2989.36    92.1 2988.93
     105 2988.44  108.422988.923     111 2989.54   115.7 2991.07   117.4 2991.38
   134.6 2992.19   143.6 2991.58   155.6 2991.85   159.6 2992.34   167.6 2994.16
   175.6 2995.56   179.6 2995.85   183.6 2995.63   191.6 2996.14   199.2 2996.26
#Mann= 3 ,-1,0
       0      .1       0    92.1    .045       0  108.42      .1       0
#XS Ineff= 2 , 0
                          135.14         2995.27
Permanent Ineff=
       F       F
Bank Sta=92.1,108.42
XS Rating Curve= 0 ,0
Exp/Cntr(USF)=0,0
Exp/Cntr=0.3,0.1

Type RM Length L Ch R = 1 ,536     ,129,129.3,130
XS GIS Cut Line= 3
2317341.63944612594639.877710053 2317367.8274526594683.781132687
2317524.18525602594767.736800532
#Sta/Elev= 30
       0 2992.33     2.8 2992.31    10.8 2992.83    20.1 2992.05    29.5 2991.64
    38.8 2991.47    51.5 2991.88    54.1 2991.79    60.6 2990.74    64.2 2989.64
      79  2986.4      872985.721    92.4  2985.3    96.9  2985.7     106 2987.54
   110.5 2987.65   119.6 2987.27   128.7 2987.99   138.1 2988.43   142.3 2988.75
   146.9 2989.32   149.9  2989.4     164 2989.18   174.1 2989.24   189.4 2990.71
   201.3 2992.39   205.9 2992.81   211.9 2992.49   223.7 2992.27   228.6 2992.38
#Mann= 3 ,-1,0
       0      .1       0      87    .045       0    96.9      .1       0
Bank Sta=87,96.9
XS Rating Curve= 0 ,0
Exp/Cntr(USF)=0,0
Exp/Cntr=0.3,0.1

Type RM Length L Ch R = 1 ,407     ,47.6,46,45
XS GIS Cut Line= 2
2317280.83247643594777.3698236782317407.69174973594856.060790518
#Sta/Elev= 30
       0 2987.19    14.8  2986.5    16.8 2986.53    27.5 2987.21    28.4 2987.14
      30 2986.85    32.2 2986.18    37.1 2983.92    40.1 2983.25    43.82982.837
      51 2982.35    52.8 2982.42    55.7 2982.79    60.3 2983.52    65.1  2983.8
    67.9 2983.71    74.5 2983.21    80.7  2983.6    89.4 2983.61    98.1 2983.46
   102.8 2984.45   105.9 2984.79   118.5 2985.21   124.3 2985.54   126.3 2985.75
   130.1 2986.45   136.2 2988.35   138.8 2988.78   145.1 2989.39   149.3 2990.24
#Mann= 3 ,-1,0
       0      .1       0    43.8    .045       0    55.7      .1       0
Bank Sta=43.8,55.7
XS Rating Curve= 0 ,0
Exp/Cntr(USF)=0,0
Exp/Cntr=0.3,0.1

Type RM Length L Ch R = 1 ,361     ,82,79.7,80.1
XS GIS Cut Line= 2
2317243.14477192594817.1352700072317410.14618512594895.334344441
#Sta/Elev= 30
       0 2984.58     9.5 2984.98      19 2985.89    21.9 2986.02    28.4 2985.33
    30.9 2985.37    36.5  2985.8    37.8 2985.74    40.9  2985.4    45.3 2983.18
    49.7 2981.81      55  2981.6    57.92981.297    66.1 2981.01      70 2981.33
      79 2982.51    85.1 2982.94    93.9 2982.89   106.1 2982.36     116 2982.17
   122.7 2982.46   129.2 2983.03   138.1 2982.91   142.5 2984.36   146.9 2986.85
   151.3 2987.81   164.6 2988.01   177.8  2986.2   182.2 2986.17   184.4  2986.5
#Mann= 4 ,-1,0
       0     .12       0      40      .1       0    57.9    .045       0
      70      .1       0
Bank Sta=57.9,70
XS Rating Curve= 0 ,0
Exp/Cntr(USF)=0,0
Exp/Cntr=0.3,0.1

Type RM Length L Ch R = 1 ,281     ,66.6,76.1,83.7
XS GIS Cut Line= 4
 2317216.6366111 594851.595879082317236.51773172594905.274904751
2317357.54687522 594941.994206052317473.24017042  594954.3668368
#Sta/Elev= 30
       0  2984.5       6 2984.33    16.4 2983.22    22.7 2983.26      32 2983.78
    38.2 2983.73    50.7 2982.76    61.1 2982.89    73.6 2982.02    98.2  2982.4
   102.9 2982.12  114.492980.432   127.9 2980.18130.49952980.393   136.3 2980.99
   144.7  2980.6   148.8 2980.78     153  2981.5   157.2 2981.67   169.7 2981.48
   192.1 2982.39   206.5 2983.64   214.4 2984.98   222.6  2986.2   230.6  2986.6
     269 2986.75   278.9 2986.98   287.1 2987.54     295 2987.55   300.1 2987.91
#Mann= 6 ,-1,0
       0     .12       0    50.7      .1       0    98.2     .12       0
  114.49    .045       0130.4995     .12       0   214.4      .1       0
Bank Sta=114.49,130.4995
XS Rating Curve= 0 ,0
Exp/Cntr(USF)=0,0
Exp/Cntr=0.3,0.1

Type RM Length L Ch R = 1 ,205     ,65.7,66.6,67.2
XS GIS Cut Line= 6
2317221.93824326594888.0446002142317221.93824326594924.493321349
2317278.04054294595016.2285048562317317.58674193595075.659187022
2317322.34243993595073.6210307342317494.39416137595010.630039554
#Sta/Elev= 30
       0 2983.31     1.1 2983.42     9.1 2982.58    13.1 2982.75    21.1 2982.95
    33.1  2982.4    41.5 2982.36    46.6 2981.86      56 2979.69    65.4 2979.63
    70.1 2979.99    84.1 2980.27    93.5 2978.83   102.82977.842   111.3 2977.45
   115.22977.845   121.6 2979.02   145.1 2979.53   154.9 2978.78   164.3  2979.6
   177.9 2978.58   188.4 2978.48   205.6 2979.46   290.6 2979.75   311.9 2980.84
     329 2979.94   343.9 2980.22   358.8 2981.52   375.8 2983.77   403.8 2984.77
#Mann= 4 ,-1,0
       0     .12       0    13.1      .1       0   102.8    .045       0
   115.2      .1       0
#XS Ineff= 1 ,-1
  197.05   270.7 2981.55
Permanent Ineff=
       F
Bank Sta=102.8,115.2
XS Rating Curve= 0 ,0
Exp/Cntr(USF)=0,0
Exp/Cntr=0.3,0.1

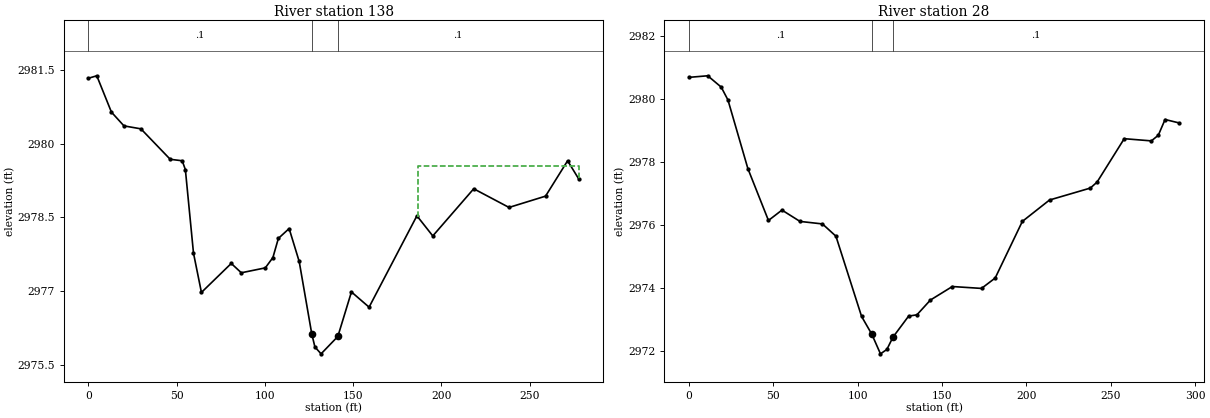
Type RM Length L Ch R = 1 ,138     ,112.2,110.1,109.2
XS GIS Cut Line= 4
2317177.74698723594896.6658254272317163.44553973594946.139737431
 2317235.0492889595081.8347396072317306.39157806595096.810913467
#Sta/Elev= 30
       0 2981.33     4.7 2981.38      13 2980.64    20.1 2980.36    29.7  2980.3
    46.3 2979.68    53.1 2979.65    54.9 2979.47    59.5 2977.77      64 2976.97
    80.9 2977.56    86.6 2977.37   100.2 2977.47   104.5 2977.68   107.6 2978.07
   113.7 2978.27   119.4  2977.6   126.5 2976.13   128.3 2975.86   131.8 2975.72
   141.32976.074     149 2976.98     159 2976.67   186.1 2978.53   195.1 2978.12
   218.3 2979.08   238.3  2978.7     259 2978.93   271.5 2979.65   277.8 2979.28
#Mann= 3 ,-1,0
       0      .1       0   126.5    .045       0   141.3      .1       0
#XS Ineff= 2 , 0
                          186.59         2979.54
Permanent Ineff=
       F       F
Bank Sta=126.5,141.3
XS Rating Curve= 0 ,0
Exp/Cntr(USF)=0,0
Exp/Cntr=0.3,0.1

Type RM Length L Ch R = 1 ,28      ,,,
XS GIS Cut Line= 4
2317082.95944726594930.1347233152317086.88995894595032.328026966
2317122.26456405 595077.248160442317252.53295113595092.408705487
#Sta/Elev= 30
       0 2980.69    11.1 2980.74    19.1 2980.38    23.1 2979.97    34.9 2977.79
    47.1 2976.14    55.1 2976.47    65.8 2976.11    79.1 2976.03    87.1 2975.64
   102.3 2973.09   108.4 2972.52   113.5  2971.9   117.3 2972.04   120.9 2972.43
   130.2  2973.1   135.1 2973.14   143.1 2973.61   156.1 2974.04   173.4 2973.98
   181.5 2974.31   197.6 2976.11   213.7 2976.79   237.9 2977.17   241.9 2977.36
     258 2978.74   274.1 2978.67   278.2 2978.85   282.2 2979.35   290.6 2979.24
#Mann= 3 ,-1,0
       0      .1       0   108.4    .045       0   120.9      .1       0
Bank Sta=108.4,120.9
XS Rating Curve= 0 ,0
Exp/Cntr(USF)=0,0
Exp/Cntr=0.3,0.1
LCMann Table=0

Chan Stop Cuts=-1
Use User Specified Reach Order=0
Composite Channel Slope=5